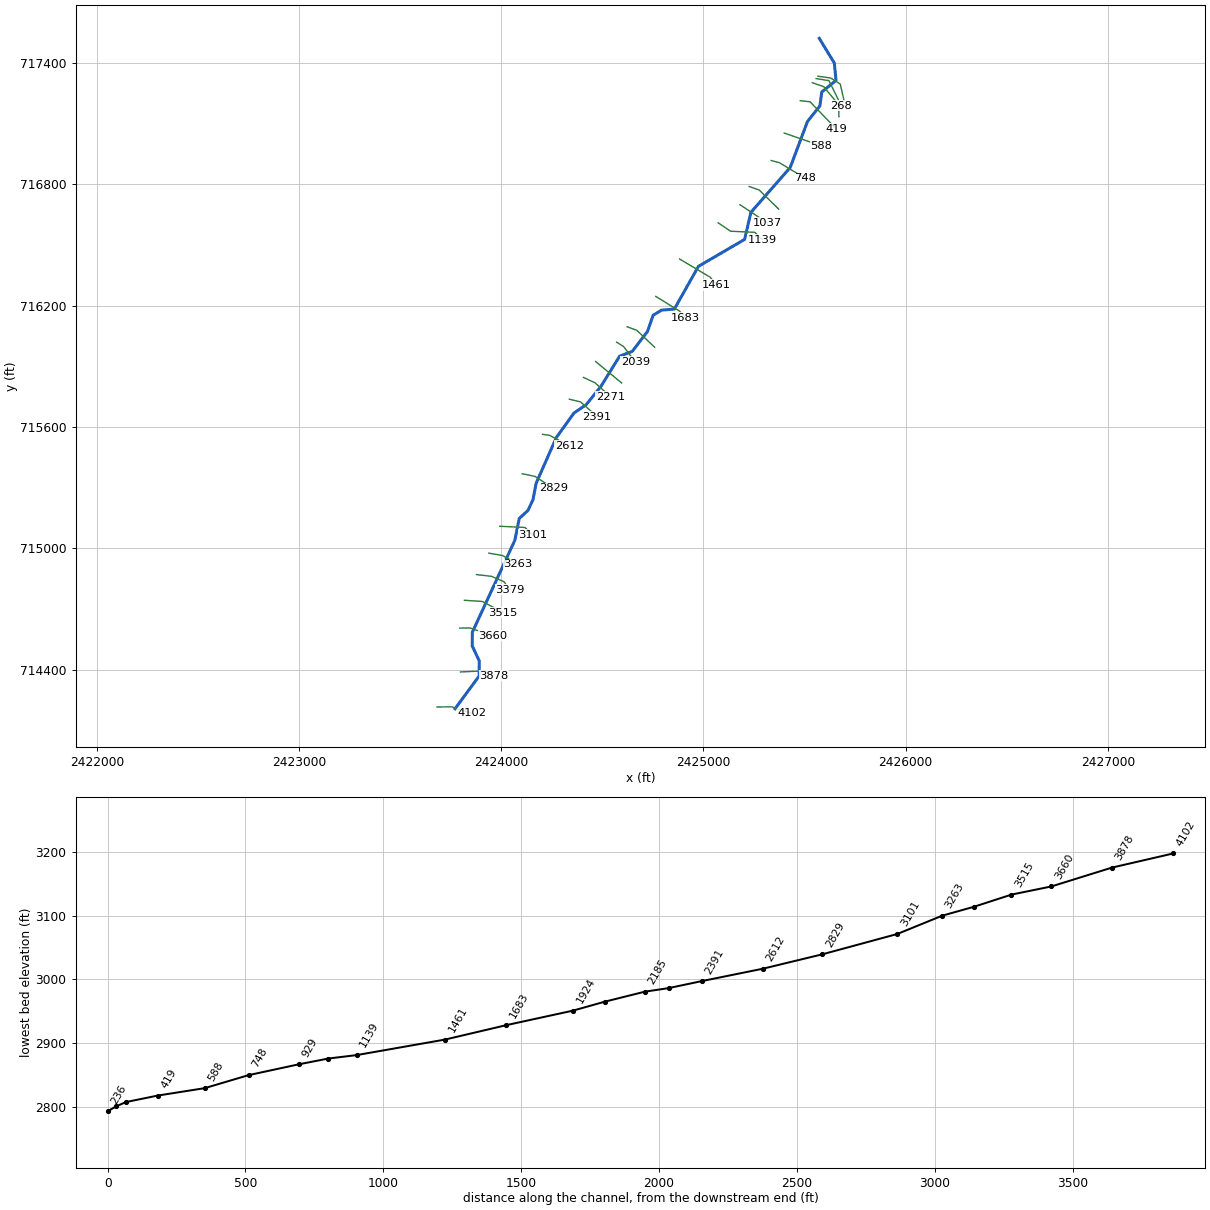
--- SFKREDCKT1.prj (project) ---

Proj Title=SFKREDCKT1
Current Plan=p01
Default Exp/Contr=0,0
English Units
Geom File=g01
Flow File=f01
Plan File=p01
BEGIN DESCRIPTION:
----------MODEL BY WOOD PLC 2022----------
AFH study
Randolph County, WV
HEC-RAS Version: RAS 6.2
Vertical Datum: NAVD88
Projection: NAD 1983 StatePlane West Virginia S FIPS 4702 (US Feet)
Terrain: 1-meter LIDAR (FEMA Region III 3DEP collected 2016-2018)
Land Use: 2019 NLCD
Hydrologic Method:
WV SIR2010-5033 regression equations
Additional Model Notes:
None
END DESCRIPTION:
DSS Export Rating Curves= 0
DSS Export Rating Curve Sorted= 0
DSS Export Volume Flow Curves= 0
DXF OffsetX= 0
DXF OffsetY= 0
DXF ScaleX= 0
DXF ScaleY= 0

--- SFKREDCKT1.p01 (plan) ---

Plan Title=Floodplain
Program Version=6.20
Short Identifier=Floodplain
Geom File=g01
Flow File=f01
Subcritical Flow
K Sum by GR= 0
Std Step Tol= 0.01
Critical Tol= 0.01
Num of Std Step Trials= 20
Max Error Tol= 0.3
Flow Tol Ratio= 0.001
Split Flow NTrial= 30
Split Flow Tol= 0.02
Split Flow Ratio= 0.02
Log Output Level= 0
Friction Slope Method= 1
Unsteady Friction Slope Method= 2
Unsteady Bridges Friction Slope Method= 1
Parabolic Critical Depth
Global Vel Dist= 0 , 0 , 0
Global Log Level= 0
CheckData=True
Encroach Param=-1 ,0,0, 0
Mapping Interval=1HOUR
Computation Time Step Use Courant=        0
Computation Time Step Use Time Series=    0
Computation Time Step Count To Double=0
Computation Time Step Max Doubling=0
Computation Time Step Max Halving=0
Computation Time Step Residence Courant=0
Run HTab= 0
Run UNet= 0
Run Sediment= 0
Run PostProcess= 0
Run WQNet= 0
Run RASMapper=-1
UNET Theta= 0
UNET Theta Warmup= 0
UNET ZTol= 0
UNET ZSATol= 0
UNET MxIter= 0
UNET Max Iter WO Improvement= 0
UNET MaxInSteps= 0
UNET DtIC= 0
UNET DtMin= 0
UNET MaxCRTS= 0
UNET WFStab= 0
UNET SFStab= 0
UNET WFX= 1
UNET SFX= 1
UNET Gravity=32.174
UNET 1D Methodology=Finite Difference
UNET DSS MLevel= 1
UNET Pardiso=0
UNET DZMax Abort= 0
UNET Use Existing IB Tables= 0
UNET Froude Reduction=False
UNET Froude Limit= 0
UNET Froude Power= 0
UNET D1 Cores= 0
UNET WindReference=Eulerian
UNET WindDragFormulation=Hsu (1988)
UNET D2 Coriolis=0
UNET D2 Cores= 0
UNET D2 Theta= 1
UNET D2 Theta Warmup= 1
UNET D2 Z Tol= 0.01
UNET D2 Volume Tol= 0.01
UNET D2 Max Iterations= 20
UNET D2 Equation= 0
UNET D2 RampUpFraction=0.1
UNET D2 TimeSlices= 1
UNET D2 Turbulence Formulation=Non-Conservative (original)
UNET D2 Eddy Viscosity=0.3
UNET D2 Transverse Eddy Viscosity=0.1
UNET D2 Smagorinsky Mixing=0
UNET D2 BCVolumeCheck=0
UNET D2 Cores=0
UNET D2 SolverType=PARDISO (Direct)
UNET D2 Minimum Iterations= 2147483647
UNET D2 Maximum Iterations= 2147483647
UNET D2 Restart Number= 10
UNET D2 Relaxation Coeff=1.3
UNET D2 SOR Precondition Iterations= 10
UNET D2 ILUT Maximum Fill= 8
UNET D2 ILUT Tolerance=1E-08
UNET D1D2 MaxIter= 0
UNET D1D2 ZTol=0.01
UNET D1D2 QTol=0.1
UNET D1D2 MinQTol=1
Write IC File= 0
Write IC File at Fixed DateTime=0
Write IC File at Sim End=0
Echo Input=False
Echo Parameters=False
Echo Output=False
Write Detailed= 0
HDF Write Warmup=0
HDF Write Time Slices=0
HDF Flush=0
HDF Compression= 1
HDF Chunk Size= 1
HDF Spatial Parts= 1
HDF Use Max Rows=0
HDF Fixed Rows= 1
Calibration Method= 0
Calibration Iterations= 20
Calibration Max Change=0.05
Calibration Tolerance=0.2
Calibration Maximum=1.5
Calibration Minimum=0.5
Calibration Optimization Method= 1
WQ AD Non Conservative
WQ ULTIMATE=-1
WQ Max Comp Step=1HOUR
WQ Output Interval=15MIN
WQ Output Selected Increments= 0
WQ Output face flow=0
WQ Output face velocity=0
WQ Output face area=0
WQ Output face dispersion=0
WQ Output cell volume=0
WQ Output cell surface area=0
WQ Output cell continuity=0
WQ Output cumulative cell continuity=0
WQ Output face conc=0
WQ Output face dconc_dx=0
WQ Output face courant=0
WQ Output face peclet=0
WQ Output face adv mass=0
WQ Output face disp mass=0
WQ Output cell mass=0
WQ Output cell source sink temp=0
WQ Output nsm pathways=0
WQ Output nsm derived pathways=0
WQ Create Restart=0
WQ Fixed Restart=0
WQ System Summary=0
WQ Write To DSS=0
Sorting and Armoring Iterations= 10
XS Update Threshold= 0.02
Bed Roughness Predictor= 0
Hydraulics Update Threshold= 0.02
Energy Slope Method= 1
Volume Change Method= 1
Sediment Retention Method= 0
Sediment TS Multiplier= 1
Warm Up Method= 0
XS Weighting Method= 0
Number of US Weighted Cross Sections= 1
Number of DS Weighted Cross Sections= 1
Upstream XS Weight=0
Main XS Weight=1
Downstream XS Weight=0
Number of DS XS's Weighted with US Boundary= 1
Upstream Boundary Weight= 1
Weight of XSs Associated with US Boundary= 0
Number of US XS's Weighted with DS Boundary= 1
Downstream Boundary Weight= 0.5
Weight of XSs Associated with DS Boundary= 0.5
Percentile Method= 0
Sediment Output Level= 3
Mass or Volume Output= 0
Output Increment Type= 1
Profile and TS Output Increment= 1
Transport Output Increment 1
XS Output Flag= 0
XS Output Increment= 10
Read HDF5 Sediment Hotstart= 0
Sediment Hotstart Type= 0
Write Gradation File= 0
Read Gradation Hotstart= 0
Write HDF5 File= 1
Write Binary Output= 1
Write DSS Sediment File= 0
DSS Sediment Output Type= 1
SV Curve= 0
Specific Gage Flag= 0
Subcell Erosion Methods= 0
Subcell Deposition Methods= 0
Advection Scheme= 1
Matrix Solver= 0
Implicit Weighting Factor= 1
Maximum Outer Loop Convergence Iterations= 5
Convergence Maximum Absolute= 0.001
Convergence RMSE= 0.0001
Grain Fractions Max Abs Error= 0.001
Max Subgrid Regions= 1
Max Subgrid Length Scale= 3.402823E+38
Initial Layer Thickness= 3.402823E+38
Min Layer Thickness= 3.402823E+38
Max Layer Thickness= 3.402823E+38
Number of Layers= 5

--- SFKREDCKT1.f01 (steady flow) ---

Flow Title=Flow
Program Version=6.20
Number of Profiles= 1
Profile Names=P100yr
River Rch & RM=SFKREDCKT1,Main,4102
     356
River Rch & RM=SFKREDCKT1,Main,2829
     413
Boundary for River Rch & Prof#=SFKREDCKT1,Main            , 1
Up Type= 0
Dn Type= 3
Dn Slope=0.25121
DSS Import GetInterval= 0
DSS Import GetPeak= 0
DSS Import FillOption= 0

--- SFKREDCKT1.g01 (geometry) ---

Geom Title=Geometry
Program Version=6.20

River Reach=SFKREDCKT1      ,Main
Reach XY= 30
2423771.23513144714205.973546184     2423890.268      714367.715
     2423891.136      714441.9342423856.18802593714516.739710581
2423856.73584212714584.330280263     2424067.036      715039.484
      2424088.96      715147.467     2424131.474      715186.134
2424156.44071058715239.205263488     2424172.386      715321.708
     2424272.212      715547.403     2424359.452      715668.497
     2424419.784       715709.84     2424492.632      715800.122
 2424585.0219916715949.4436155522424647.61296815715973.226948216
2424723.40931617716072.654435925     2424750.853      716151.885
2424792.09662395716177.3583461122424856.00994012716182.906653888
     2424974.973      716393.962     2425203.482      716527.206
     2425234.452      716661.1182425428.70531564716882.526269141
     2425514.313      717110.337     2425575.771       717187.42
2425584.97784711717256.533807628     2425655.459      717313.462
     2425647.126      717399.399     2425572.624      717521.764

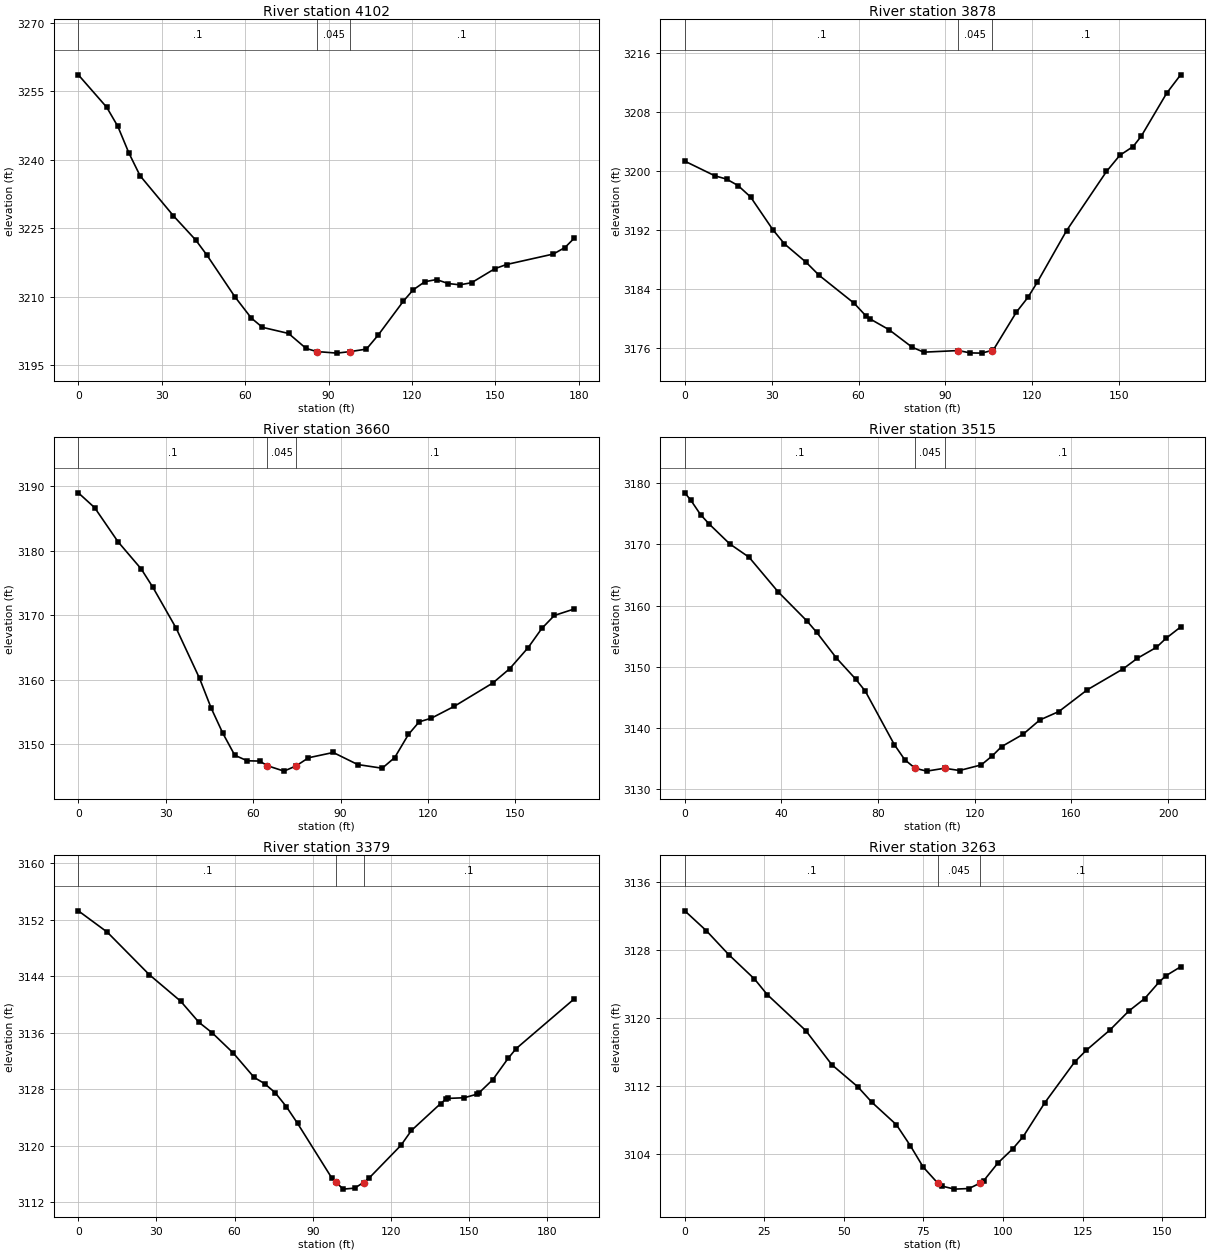
Type RM Length L Ch R = 1 ,4102    ,224.5,224,228.2
XS GIS Cut Line= 3
2423682.01853384714214.8008613852423755.86008466714215.043583069
2423855.29267463714182.992084115
#Sta/Elev= 30
       0 3258.59    10.2 3251.49    14.2  3247.3    18.2 3241.44    22.2 3236.49
    34.2 3227.71    42.2 3222.42    46.2 3219.14    56.3 3209.98    62.2 3205.32
    66.2 3203.29    75.6 3201.95    81.9 3198.67   85.69 3197.99      93 3197.64
    97.8 3197.98   103.6 3198.52   107.8 3201.57   116.9 3209.03   120.4 3211.49
   124.6 3213.28   128.8 3213.75     133 3212.88   137.2  3212.6   141.4 3213.06
   149.8 3216.14     154 3217.05   170.8 3219.34     175 3220.77   178.3  3222.8
#Mann= 3, -1 ,  0
       0     0.1       0   85.69   0.045       0    97.8     0.1       0
Bank Sta=85.69,97.8
XS Rating Curve= 0 ,0
Exp/Cntr=0.3,0.1

Type RM Length L Ch R = 1 ,3878    ,220,218.6,216.1
XS GIS Cut Line= 3
2423797.77558503714387.8519848322423919.31516174714393.321265784
2423962.46171147714369.013350442
#Sta/Elev= 30
       0 3201.28    10.4 3199.29    14.4 3198.85    18.4 3197.97    22.7 3196.43
    30.4 3191.99    34.4 3190.07    41.9 3187.57    46.4  3185.8    58.5 3182.01
    62.5 3180.32      64 3179.89    70.5 3178.44    78.5 3176.06    82.5 3175.39
    94.5 3175.61    98.5 3175.29   102.5 3175.26   105.9 3175.61   106.5 3175.67
   114.5 3180.82   118.5 3182.83   121.7 3184.86   131.8 3191.85   145.6 3199.88
   150.2 3202.07   154.8 3203.26   157.6 3204.66   166.4  3210.5   171.2 3212.98
#Mann= 3, -1 ,  0
       0     0.1       0    94.5   0.045       0   105.9     0.1       0
Bank Sta=94.5,105.9
XS Rating Curve= 0 ,0
Exp/Cntr(USF)=0,0
Exp/Cntr=0.3,0.1

Type RM Length L Ch R = 1 ,3660    ,145.4,144.9,143.6
XS GIS Cut Line= 3
2423794.57626538714604.739071923 2423845.6228876714605.346769806
2423958.65469394714567.669501026
#Sta/Elev= 30
       0 3188.95     5.6 3186.65    13.6 3181.38    21.6 3177.14    25.6  3174.3
    33.6 3167.95    41.6  3160.2    45.6 3155.58    49.6 3151.68    53.7 3148.27
      58 3147.41    62.2 3147.37   64.923146.647    70.6 3145.81    74.8 3146.63
      79 3147.88    87.5  3148.7    95.9 3146.83   104.3 3146.26   108.6 3147.91
   113.3 3151.49     117 3153.45   121.2 3154.02   129.1 3155.87   142.3 3159.48
   148.1  3161.7   154.4 3164.95   159.1 3167.93   163.4 3169.94   170.2 3170.94
#Mann= 3, -1 ,  0
       0     0.1       0   64.92   0.045       0    74.8     0.1       0
Bank Sta=64.92,74.8
XS Rating Curve= 0 ,0
Exp/Cntr(USF)=0,0
Exp/Cntr=0.3,0.1

Type RM Length L Ch R = 1 ,3515    ,135.4,136.1,136.2
XS GIS Cut Line= 3
2423817.64652379714742.4000668852423906.02783246714736.591109279
2424008.95298534714681.791017164
#Sta/Elev= 30
       0 3178.43     2.5 3177.22     6.5 3174.88      10 3173.37    18.6 3170.09
    26.6 3167.91    38.6 3162.27    50.6 3157.48    54.6 3155.64    62.7 3151.47
    70.7 3148.02    74.7 3146.04    86.7 3137.32      91 3134.86    95.3 3133.45
   100.1 3132.98   107.5 3133.45   113.7 3133.08   122.7    3134   127.3 3135.49
   131.1 3136.98     140    3139   146.9 3141.33   154.8 3142.71   166.6 3146.27
   181.4 3149.68   187.3 3151.41   195.2  3153.2   199.1 3154.65   205.2 3156.52
#Mann= 3, -1 ,  0
       0     0.1       0    95.3   0.045       0   107.5     0.1       0
Bank Sta=95.3,107.5
XS Rating Curve= 0 ,0
Exp/Cntr=0.3,0.1

Type RM Length L Ch R = 1 ,3379    ,116.1,115.6,114.8
XS GIS Cut Line= 4
2423877.12784435 714869.518694922423952.07724999714860.740836602
2424012.84703835714834.4072616472424041.88149278714795.244509152
#Sta/Elev= 30
       0 3153.24    11.1 3150.23    27.2 3144.23    39.3 3140.46    46.3 3137.48
    51.4 3135.99    59.5 3133.13    67.5 3129.69    71.5 3128.81    75.6 3127.52
    79.9 3125.54    84.2 3123.18    97.4 3115.42   99.063114.829   101.7 3113.89
   106.1 3114.03  109.513114.823   111.7 3115.47   123.9 3120.09   127.9 3122.18
   139.1 3125.98     141 3126.57   142.1 3126.72   148.2 3126.81   153.2 3127.33
     154 3127.55   159.2 3129.39     165 3132.36   168.1 3133.75   190.4 3140.78
#Mann= 3, -1 ,  0
       0     0.1       0   99.06   0.045       0  109.51     0.1       0
Bank Sta=99.06,109.51
XS Rating Curve= 0 ,0
Exp/Cntr(USF)=0,0
Exp/Cntr=0.3,0.1

Type RM Length L Ch R = 1 ,3263    ,158.6,162.4,165
XS GIS Cut Line= 3
2423938.60066378714975.4347808912424006.05512885714963.888521104
 2424082.0173643714920.741971371
#Sta/Elev= 30
       0 3132.58     6.8 3130.23    13.8 3127.43    21.9 3124.56    25.9 3122.73
      38  3118.5    46.2 3114.48    54.4 3111.87    58.8 3110.06    66.5 3107.42
    70.9 3104.94    74.9 3102.45   79.493100.555    80.8 3100.21    84.7 3099.85
    89.3 3099.92    92.83100.563    93.9 3100.83    98.4 3102.93   103.1 3104.61
   106.3 3106.01   113.1    3110   122.5  3114.8   126.1 3116.16   133.6 3118.57
   139.5 3120.79   144.5 3122.26   149.1 3124.23   151.2 3124.95   155.8    3126
#Mann= 3, -1 ,  0
       0     0.1       0   79.49   0.045       0    92.8     0.1       0
Bank Sta=79.49,92.8
XS Rating Curve= 0 ,0
Exp/Cntr(USF)=0,0
Exp/Cntr=0.3,0.1

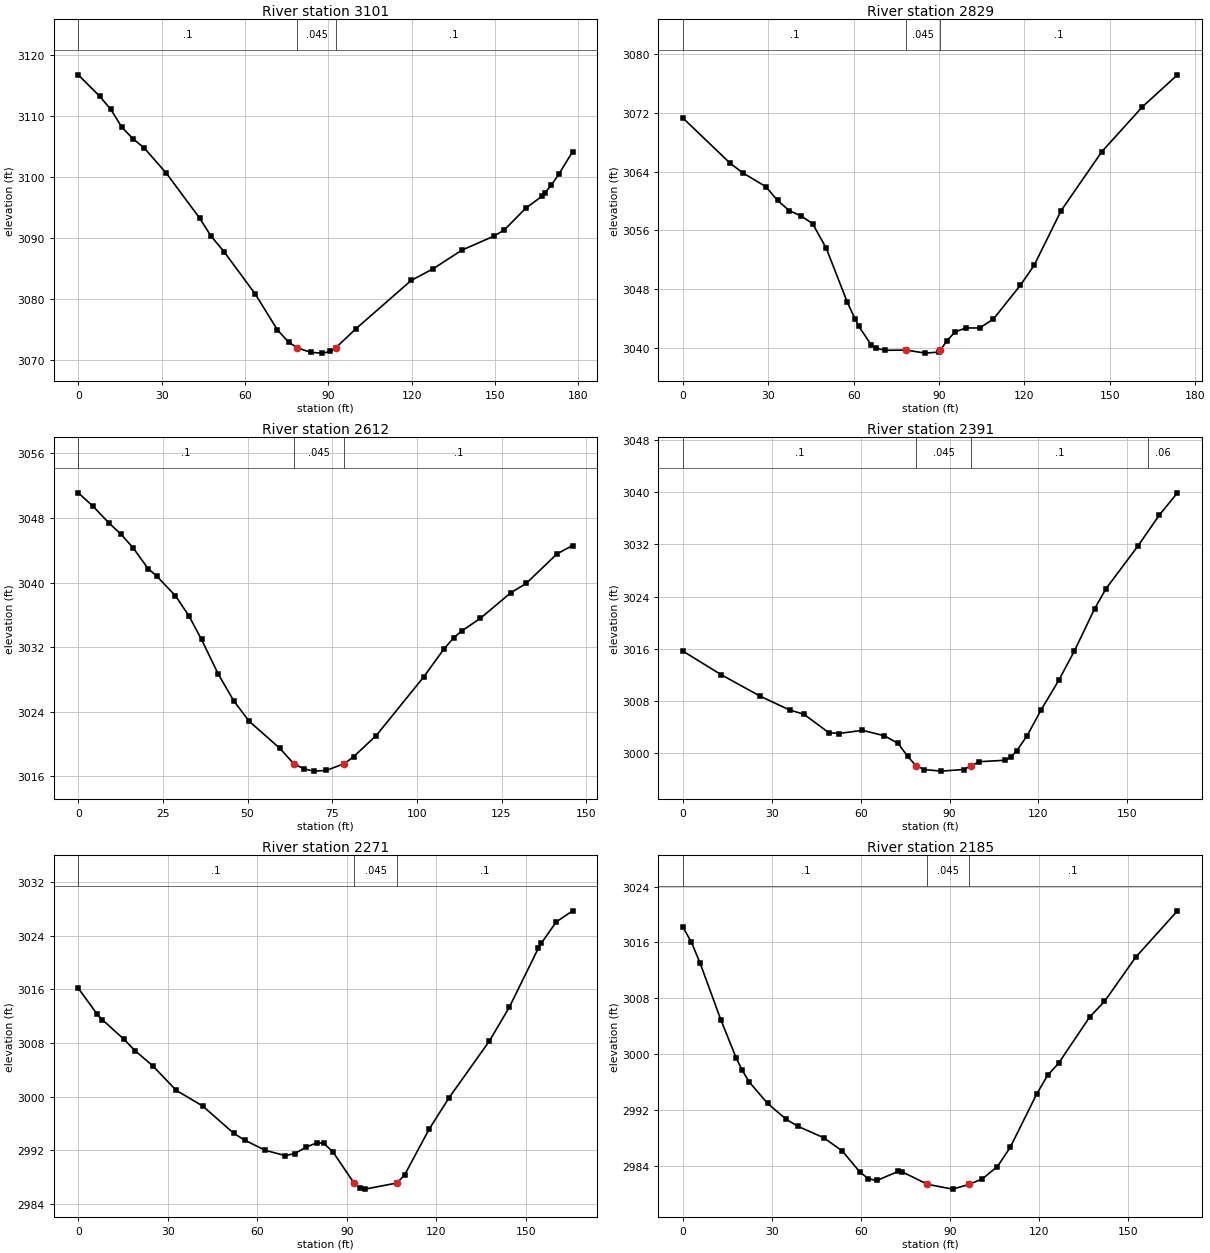
Type RM Length L Ch R = 1 ,3101    ,274.7,272,267.8
XS GIS Cut Line= 3
2423992.52118861715108.4527555182424117.00121304715102.500954263
2424155.28886382715065.404597676
#Sta/Elev= 30
       0  3116.7     7.7  3113.2    11.7 3111.05    15.7 3108.12    19.7 3106.25
    23.7 3104.75    31.7 3100.61    43.7 3093.25    47.7 3090.38    52.5 3087.75
    63.7 3080.85    71.7 3074.97    75.7 3072.99   78.853072.053    83.7 3071.31
    87.8 3071.19    90.7 3071.46   92.653072.054    99.8 3075.13   119.8 3083.07
   127.8 3085.01     138 3088.02   149.5 3090.31   153.3 3091.32     161 3094.88
   166.8 3096.82     168 3097.43   170.2 3098.64   173.1 3100.56   177.9 3104.14
#Mann= 3, -1 ,  0
       0     0.1       0   78.85   0.045       0   92.65     0.1       0
Bank Sta=78.85,92.65
XS Rating Curve= 0 ,0
Exp/Cntr=0.3,0.1

Type RM Length L Ch R = 1 ,2829    ,215.8,216.2,216.5
XS GIS Cut Line= 3
 2424103.6719049715368.1986670872424166.56863585715355.072392802
2424258.45255584715295.457230425
#Sta/Elev= 30
       0 3071.28    16.5 3065.16    20.9 3063.85    29.1 3061.95    33.2 3060.08
    37.3 3058.69    41.4 3057.98    45.5 3056.92    50.3 3053.59    57.7 3046.24
    60.4 3043.96    61.8  3042.9    66.2 3040.36    67.7 3039.98    70.9 3039.65
    78.3 3039.69    85.2 3039.27    89.8 3039.41   90.39 3039.66    92.8 3040.97
    95.7 3042.19    99.5  3042.7   104.3  3042.7   109.1 3043.91   118.6 3048.53
   123.4 3051.22   132.9 3058.68   147.2 3066.71   161.5 3072.84   173.8 3077.19
#Mann= 3, -1 ,  0
       0     0.1       0    78.3   0.045       0   90.39     0.1       0
Bank Sta=78.3,90.39
XS Rating Curve= 0 ,0
Exp/Cntr(USF)=0,0
Exp/Cntr=0.3,0.1

Type RM Length L Ch R = 1 ,2612    ,223,221.9,219.3
XS GIS Cut Line= 3
2424203.84902777715563.2602652822424239.80487132715557.762976486
2424336.19800833715505.571239861
#Sta/Elev= 30
       0 3051.12     4.4 3049.44     9.1 3047.36    12.6    3046    16.2  3044.3
    20.6 3041.74    23.2 3040.79    28.7 3038.36    32.7 3035.86    36.4 3032.95
    41.3 3028.69    45.9 3025.36    50.4 3022.84    59.5 3019.47   63.63 3017.56
    66.6 3016.92    69.5 3016.63    73.2 3016.71   78.59 3017.56    81.3 3018.41
      88 3021.04     102 3028.29   107.9 3031.71   110.9 3033.17   113.2 3033.98
   118.7 3035.55   127.8 3038.75   132.3 3039.89   141.4 3043.56     146 3044.59
#Mann= 3, -1 ,  0
       0     0.1       0   63.63   0.045       0   78.59     0.1       0
Bank Sta=63.63,78.59
XS Rating Curve= 0 ,0
Exp/Cntr=0.3,0.1

Type RM Length L Ch R = 1 ,2391    ,119.6,119.8,119.6
XS GIS Cut Line= 3
2424336.50208347 715736.969959412424392.02016172715723.465561998
2424474.19938659715650.596501279
#Sta/Elev= 30
       0 3015.59    12.8    3012      26 3008.69      36 3006.55    40.8 3005.91
    49.2 3003.08    52.5 3002.94    60.6 3003.43      68  3002.6    72.6 3001.43
    75.9 2999.41    78.7 2997.97    78.7 2997.96    81.5  2997.4    87.2 2997.16
    94.8 2997.41   97.292997.964   100.1 2998.61   108.8 2998.83   110.8 2999.35
   112.7 3000.28   116.2 3002.59   120.9 3006.54   126.9 3011.12   132.2 3015.64
     139 3022.11   142.9 3025.23   153.6 3031.73   160.9 3036.54     167 3039.94
#Mann= 4, -1 ,  0
       0     0.1       0    78.7   0.045       0   97.29     0.1       0
  157.14    0.06       0
Bank Sta=78.7,97.29
XS Rating Curve= 0 ,0
Exp/Cntr(USF)=0,0
Exp/Cntr=0.3,0.1

Type RM Length L Ch R = 1 ,2271    ,85.3,85.8,86
XS GIS Cut Line= 3
2424406.33744267 715844.507684672424463.18928102715818.342597056
  2424540.013652715749.511651125
#Sta/Elev= 30
       0 3016.16     6.4 3012.24       8 3011.48    15.2 3008.59      19 3006.85
      25 3004.57    32.8 3000.94    41.7 2998.59    52.1 2994.53    55.8  2993.5
    62.6    2992    69.3  2991.2    72.6  2991.5    76.3 2992.45      80 2993.11
    82.3 2993.03    85.4 2991.73    92.4 2987.12    94.3 2986.43    96.1  2986.2
   106.9 2987.12   109.4 2988.33   117.6 2995.13   124.3 2999.83   137.8 3008.27
   144.5 3013.33   154.2  3022.1   155.2 3022.85   160.2 3026.03   165.7 3027.69
#Mann= 3, -1 ,  0
       0     0.1       0    92.4   0.045       0   106.9     0.1       0
Bank Sta=92.4,106.9
XS Rating Curve= 0 ,0
Exp/Cntr=0.3,0.1

Type RM Length L Ch R = 1 ,2185    ,146.4,145.8,143.8
XS GIS Cut Line= 2
2424466.36479324715923.3313858172424595.01530279715817.333623798
#Sta/Elev= 30
       0 3018.15     2.8 3016.03     5.7 3013.07    12.7 3004.94    17.9 2999.44
    19.9  2997.7    22.3    2996    28.5 2992.92    34.8 2990.64    38.6 2989.67
    47.4 2988.01    53.7  2986.1    59.6 2983.09    62.5 2982.12    65.3 2981.88
    72.6 2983.18    73.9 2983.11    82.4 2981.33    90.9 2980.64   96.33 2981.31
   100.8 2982.08     106 2983.88   110.3 2986.62   119.3 2994.32   122.9 2996.94
   126.7 2998.73   137.1 3005.31   142.1 3007.54   152.6 3013.87   166.7 3020.53
#Mann= 3, -1 ,  0
       0     0.1       0    82.4   0.045       0   96.33     0.1       0
Bank Sta=82.4,96.33
XS Rating Curve= 0 ,0
Exp/Cntr(USF)=0,0
Exp/Cntr=0.3,0.1

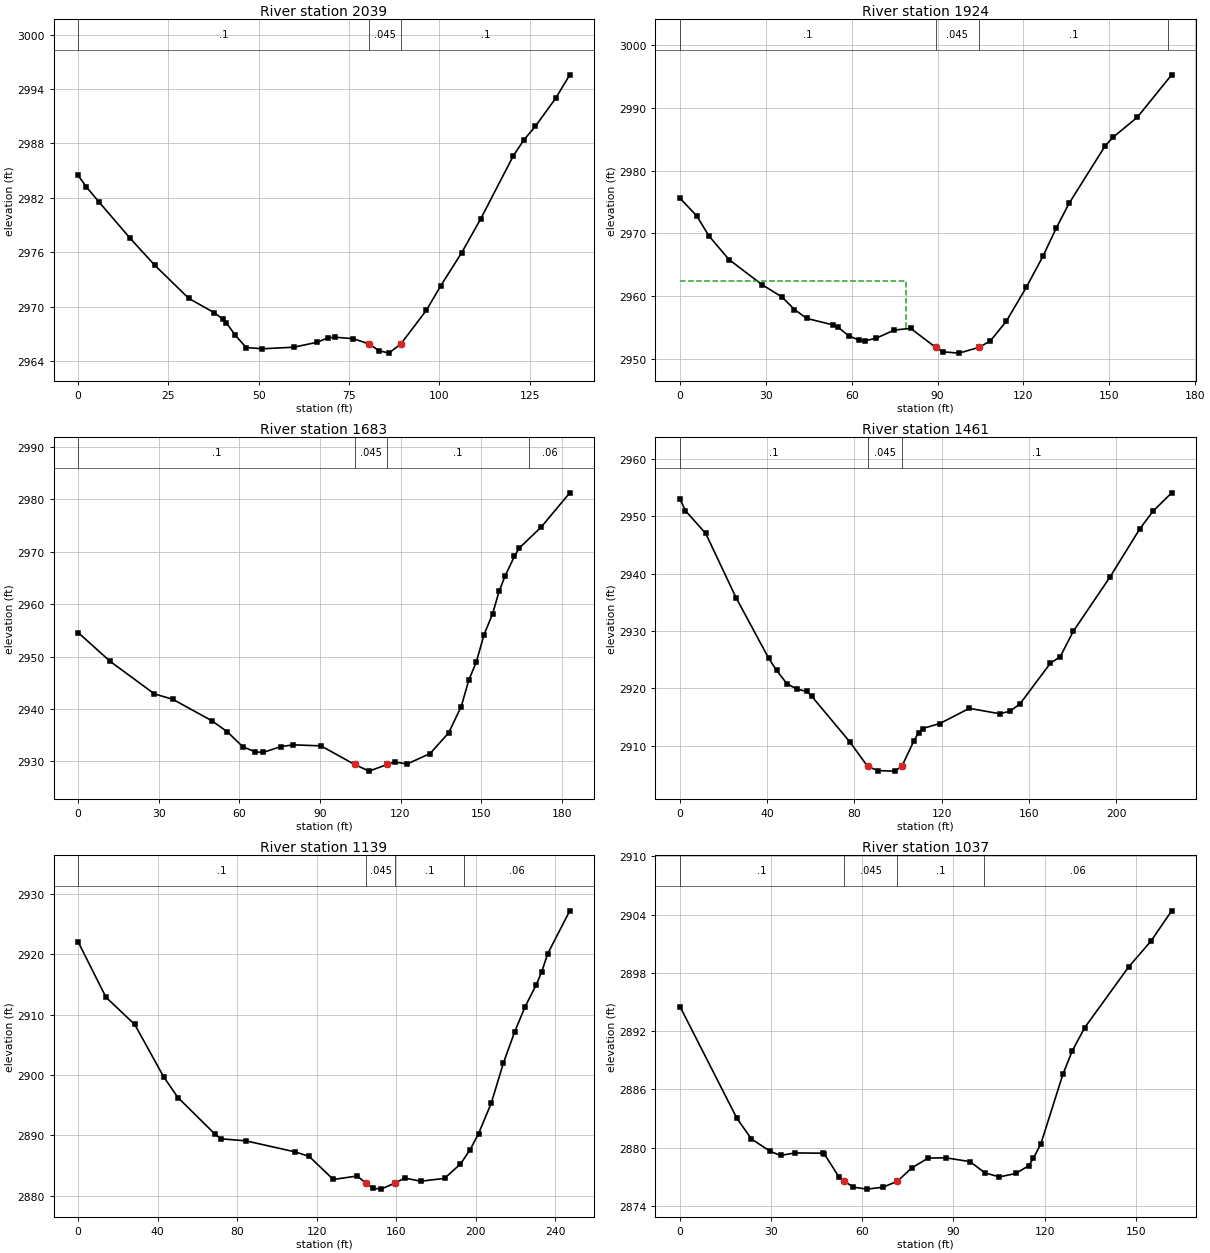
Type RM Length L Ch R = 1 ,2039    ,113.8,115,114.5
XS GIS Cut Line= 3
2424570.22550361716019.0712998982424604.41833007715997.700783363
2424662.54613505715921.621744494
#Sta/Elev= 30
       0 2984.48     2.3  2983.2     5.7 2981.59    14.4 2977.55    21.2 2974.59
    30.6 2970.94    37.6 2969.37      40 2968.68      41 2968.27    43.4 2966.92
    46.5 2965.52      51 2965.38    59.7 2965.55    66.2  2966.1    69.1 2966.58
    71.2 2966.65    76.2 2966.49    80.5 2965.91    83.3 2965.17      86  2964.9
   89.32  2965.9    96.4 2969.62   100.4 2972.33   106.2 2975.98   111.5 2979.73
   120.4 2986.58   123.3 2988.34   126.6  2989.9   132.2 2992.98   136.1 2995.56
#Mann= 3, -1 ,  0
       0     0.1       0    80.5   0.045       0   89.32     0.1       0
Bank Sta=80.5,89.32
XS Rating Curve= 0 ,0
Exp/Cntr(USF)=0,0
Exp/Cntr=0.3,0.1

Type RM Length L Ch R = 1 ,1924    ,238.5,241.6,241.1
XS GIS Cut Line= 3
2424622.68581046716095.1422679062424670.08624537716077.519029283
2424758.20243849715994.264419236
#Sta/Elev= 30
       0 2975.61     5.9 2972.76    10.1  2969.6    17.1 2965.83    28.6 2961.84
    35.7 2959.83      40 2957.85    44.3 2956.43    53.4  2955.4    55.1 2955.08
    58.9 2953.67    62.7 2952.94    64.5 2952.85    68.5 2953.26    74.9 2954.57
    80.6 2954.84   89.322951.816    91.8  2951.1    97.5 2950.89  104.532951.814
   108.5 2952.86     114 2955.96     121 2961.38   126.8 2966.32   131.5 2970.86
     136 2974.82   148.5 2983.91   151.3 2985.33   159.8 2988.52   171.8  2995.3
#Mann= 4, -1 ,  0
       0     0.1       0   89.32   0.045       0  104.53     0.1       0
  170.57    0.06       0
#XS Ineff= 2 , 0
           79.02 2962.44
Permanent Ineff=
       F       F
Bank Sta=89.32,104.53
XS Rating Curve= 0 ,0
Exp/Cntr(USF)=0,0
Exp/Cntr=0.3,0.1

Type RM Length L Ch R = 1 ,1683    ,221.8,221.9,221.8
XS GIS Cut Line= 3
 2424764.0309332716245.4226922992424881.28489935716172.891985905
2424911.25245307716139.096789895
#Sta/Elev= 30
       0 2954.58    11.9 2949.08    28.4 2942.86    35.2 2941.84    49.7 2937.76
    55.5 2935.65    61.3 2932.77      66 2931.78    68.9  2931.7    75.4 2932.79
    80.1 2933.14    90.4 2932.94  102.932929.388   108.3 2928.12  115.022929.389
   117.8 2929.85   122.5 2929.49     131 2931.48   137.9 2935.41   142.6 2940.45
   145.4 2945.46   148.2 2948.94   151.1 2954.18   154.3 2958.19   156.7 2962.47
   158.9 2965.34   162.4 2969.13   164.2  2970.7   172.4 2974.73     183 2981.25
#Mann= 4, -1 ,  0
       0     0.1       0  102.93   0.045       0  115.02     0.1       0
  167.87    0.06       0
Bank Sta=102.93,115.02
XS Rating Curve= 0 ,0
Exp/Cntr(USF)=0,0
Exp/Cntr=0.3,0.1

Type RM Length L Ch R = 1 ,1461    ,321.3,321.4,328.1
XS GIS Cut Line= 3
2424882.04742639716429.9618382152425033.19056935716340.331898302
 2425064.8690732716301.880580498
#Sta/Elev= 30
       0 2953.04     2.5 2950.98    11.8 2947.02    25.7 2935.82    40.7 2925.22
    44.3 2923.12      49 2920.81    53.6 2919.85    58.3 2919.43    60.5 2918.56
      78 2910.59   86.042906.353    90.8 2905.62    98.5 2905.53  101.742906.354
   107.2 2910.74   109.4 2912.24   111.3 2912.97   119.2 2913.84   132.7 2916.49
   146.6 2915.55   151.3 2915.98   155.9 2917.25   169.9 2924.37   174.4 2925.51
   180.4 2929.94   197.1 2939.34   210.9 2947.82     217 2950.92   225.5 2954.11
#Mann= 3, -1 ,  0
       0     0.1       0   86.04   0.045       0  101.74     0.1       0
Bank Sta=86.04,101.74
XS Rating Curve= 0 ,0
Exp/Cntr=0.3,0.1

Type RM Length L Ch R = 1 ,1139    ,107.3,102.5,98.4
XS GIS Cut Line= 4
2425072.57854077716609.236100039 2425134.2118755 716567.67960566
2425253.89318387716562.3078329372425292.11907105716525.226094909
#Sta/Elev= 30
       0 2922.04      14 2912.86    28.5 2908.35      43 2899.71    50.2 2896.26
    68.9 2890.19    71.8 2889.42    84.3 2889.09   109.3 2887.25   116.3  2886.5
   128.4 2882.69   140.4 2883.26  144.742882.117   148.4 2881.23   152.4 2881.09
  159.612882.118   164.4 2882.92   172.4  2882.4   184.4 2882.87   192.4 2885.26
   197.3 2887.64   201.5 2890.28   207.9 2895.33     214 2901.97   219.6 2907.06
   224.8 2911.21   230.5 2914.91   233.3 2917.09   236.3 2920.07   247.4 2927.17
#Mann= 4, -1 ,  0
       0     0.1       0  144.74   0.045       0  159.61     0.1       0
  194.14    0.06       0
Bank Sta=144.74,159.61
XS Rating Curve= 0 ,0
Exp/Cntr=0.3,0.1

Type RM Length L Ch R = 1 ,1037    ,109.8,107.8,106.6
XS GIS Cut Line= 2
 2425180.5528284716698.7444390772425315.46175855716609.412850195
#Sta/Elev= 30
       0 2894.53    18.7 2883.03    23.5 2880.89    29.7 2879.61    33.1 2879.19
    37.9 2879.45      47 2879.42    47.5 2879.34    52.3 2876.98   54.092876.523
    57.1 2875.92    61.5 2875.72    66.7 2875.91    71.5 2876.52    76.3 2877.91
    81.7 2878.92    87.4 2878.95    95.5 2878.55   100.3  2877.4   105.1 2876.98
   110.5 2877.33   114.7 2878.12   116.3 2878.89   118.8 2880.42     126 2887.54
   129.1 2889.97   133.2 2892.36   147.7 2898.63     155 2901.27   161.8 2904.39
#Mann= 4, -1 ,  0
       0     0.1       0   54.09   0.045       0    71.5     0.1       0
     100    0.06       0
Bank Sta=54.09,71.5
XS Rating Curve= 0 ,0
Exp/Cntr(USF)=0,0
Exp/Cntr=0.3,0.1

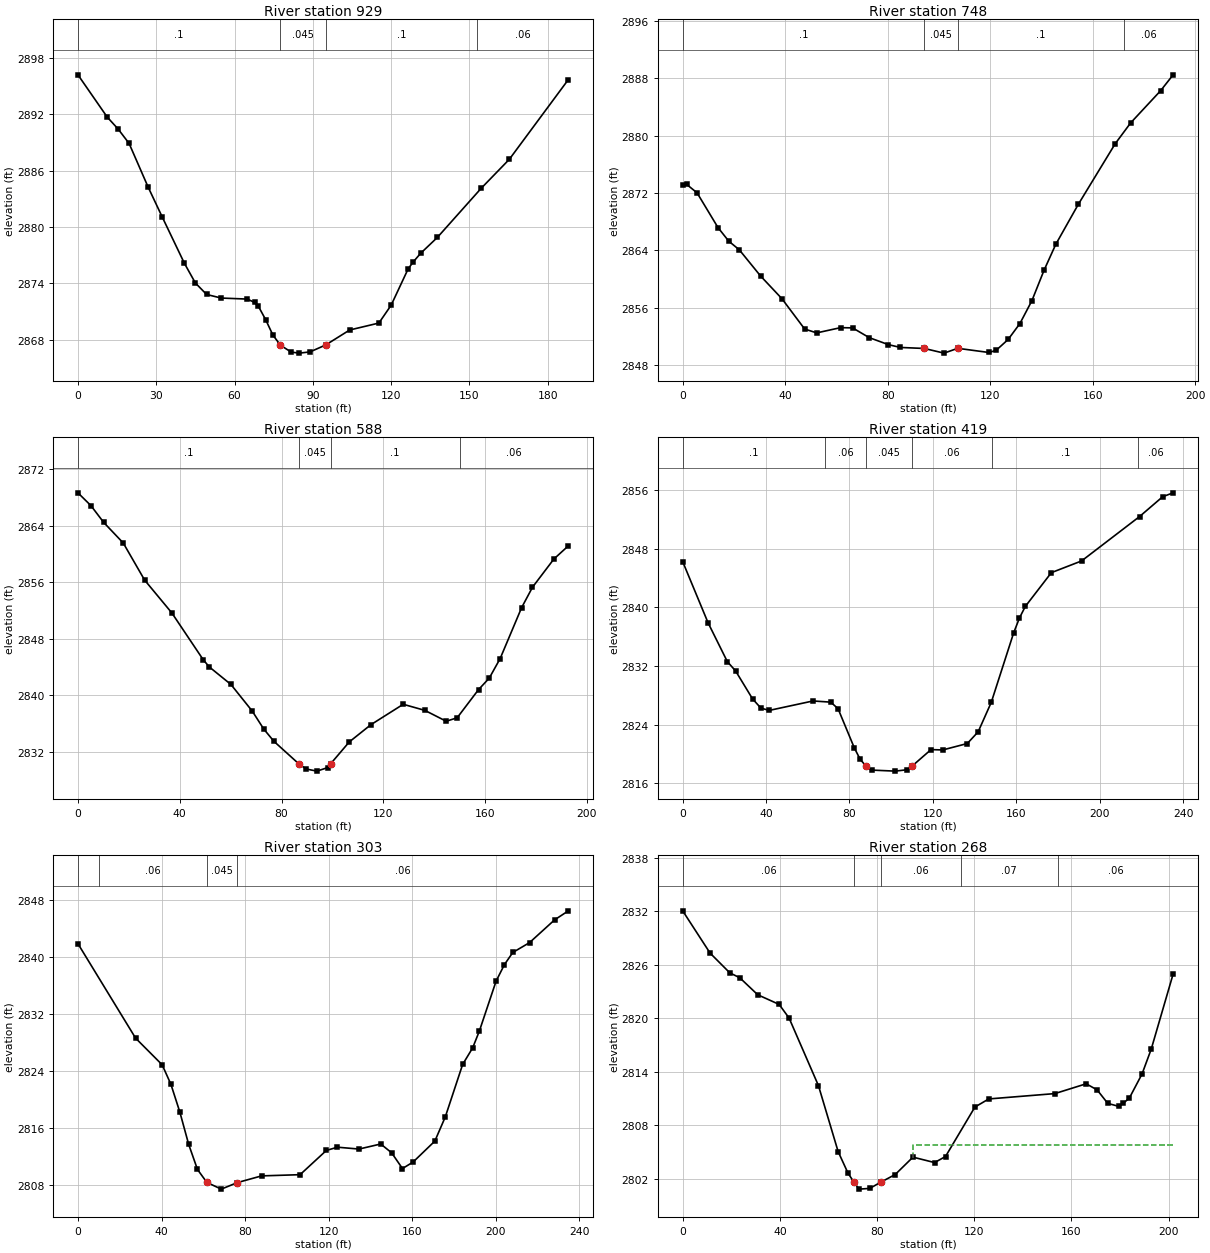
Type RM Length L Ch R = 1 ,929     ,179.2,181.3,182.4
XS GIS Cut Line= 3
2425225.69457596716789.0204998162425275.71086267716771.422176713
2425372.03852596716676.946968479
#Sta/Elev= 30
       0 2896.18    11.2 2891.69    15.4 2890.41    19.6 2888.88    26.9 2884.23
    32.3 2881.05    40.8 2876.12      45 2874.03    49.3 2872.81    54.9 2872.43
    64.9 2872.32    67.7 2871.96    69.1 2871.57    71.9 2870.14    74.7 2868.49
    77.6 2867.41    81.7 2866.68    84.8 2866.57    88.9  2866.7   94.94 2867.44
   104.1 2869.03   115.3 2869.77     120 2871.67   126.5 2875.53   128.5 2876.29
   131.3 2877.19   137.7 2878.88   154.5 2884.11   165.3  2887.2   187.9 2895.68
#Mann= 4, -1 ,  0
       0     0.1       0    77.6   0.045       0   94.94     0.1       0
  153.02    0.06       0
Bank Sta=77.6,94.94
XS Rating Curve= 0 ,0
Exp/Cntr(USF)=0,0
Exp/Cntr=0.3,0.1

Type RM Length L Ch R = 1 ,748     ,158,159.2,160.6
XS GIS Cut Line= 3
2425334.81565515716917.6657607092425375.56966655716906.551030328
2425503.38906592716829.674145196
#Sta/Elev= 30
       0 2873.16     1.5  2873.2     5.6 2872.02    13.8 2867.16      18 2865.27
    22.1 2864.07    30.4 2860.42    38.7 2857.27    47.6 2853.03    52.3 2852.49
    61.6 2853.22    66.3 2853.19    72.8 2851.83    80.3 2850.85      85 2850.46
    94.3 2850.32     102 2849.67  107.352850.341   119.5 2849.76   122.3 2850.05
     127 2851.57   131.6 2853.79   136.3 2856.99     141  2861.2   145.6 2864.83
   154.4 2870.41   168.8 2878.86   174.8 2881.75   186.5 2886.24   191.4 2888.46
#Mann= 4, -1 ,  0
       0     0.1       0    94.3   0.045       0  107.35     0.1       0
  172.24    0.06       0
Bank Sta=94.3,107.35
XS Rating Curve= 0 ,0
Exp/Cntr(USF)=0,0
Exp/Cntr=0.3,0.1

Type RM Length L Ch R = 1 ,588     ,174.4,169.6,165.2
XS GIS Cut Line= 2
 2425399.3810649717053.2277231382425581.50812061716990.330992189
#Sta/Elev= 30
       0 2868.63     5.1 2866.82    10.1 2864.45    17.8 2861.53    26.2 2856.28
    36.9 2851.63    49.2 2845.02    51.6 2843.99    60.1 2841.51    68.5 2837.73
      73  2835.2      77 2833.46   86.82 2830.26    89.7 2829.54    93.9 2829.24
    98.2 2829.75   99.262830.266   106.6 2833.37   115.1 2835.81   127.8  2838.7
   136.3 2837.84   144.7  2836.3     149 2836.79   157.4 2840.78   161.6  2842.4
   165.9 2845.18   174.3 2852.36   178.6 2855.27     187 2859.26   192.7 2861.13
#Mann= 4, -1 ,  0
       0     0.1       0   86.82   0.045       0   99.26     0.1       0
     150    0.06       0
Bank Sta=86.82,99.26
XS Rating Curve= 0 ,0
Exp/Cntr(USF)=0,0
Exp/Cntr=0.3,0.1

Type RM Length L Ch R = 1 ,419     ,113.1,116.3,116
XS GIS Cut Line= 3
2425478.89983228717213.4457231472425527.06366392717207.888357956
2425656.73551836717073.585365859
#Sta/Elev= 30
       0 2846.26    12.2 2837.89    21.4 2832.61    25.4 2831.32    33.5 2827.52
    37.5 2826.26    41.5 2825.94    62.5 2827.23      71 2827.07    74.5 2826.18
    82.3 2820.83    85.1 2819.27      88 2818.31    90.8 2817.79   101.9 2817.65
   107.7 2817.84  109.922818.316   119.1 2820.59   124.7 2820.54   136.5 2821.42
   141.7 2823.02     148 2827.05   158.7 2836.51   161.5 2838.56   164.3 2840.13
   176.8 2844.75   191.3 2846.35   219.1 2852.41   230.2 2855.12   235.2 2855.65
#Mann= 6, -1 ,  0
       0     0.1       0   68.48    0.06       0      88   0.045       0
  109.92    0.06       0  148.48     0.1       0  218.48    0.06       0
Bank Sta=88,109.92
XS Rating Curve= 0 ,0
Exp/Cntr(USF)=0,0
Exp/Cntr=0.3,0.1

Type RM Length L Ch R = 1 ,303     ,37.7,34.6,35.9
XS GIS Cut Line= 4
 2425538.0614933717302.3099770252425594.57739647717282.863644751
2425668.71653826717192.9243579852425669.93193403717134.585361164
#Sta/Elev= 30
       0 2841.88    27.6 2828.61    40.3 2824.87    44.5 2822.12    48.8 2818.19
      53 2813.68    57.2 2810.16   61.692808.344    68.6  2807.4    76.3 2808.32
    87.9 2809.26   106.3 2809.43   118.9 2812.84   124.2 2813.29   134.5 2813.03
   144.9 2813.74   150.1 2812.51   155.3 2810.29   160.4 2811.21   170.8 2814.15
   175.8 2817.55   184.1 2824.92   188.9 2827.25   192.1 2829.61   200.1 2836.62
   204.1 2838.95   208.1 2840.65   216.1 2842.03   228.1 2845.23   234.7  2846.5
#Mann= 4, -1 ,  0
       0     0.1       0      10    0.06       0   61.69   0.045       0
    76.3    0.06       0
Bank Sta=61.69,76.3
XS Rating Curve= 0 ,0
Exp/Cntr(USF)=0,0
Exp/Cntr=0.3,0.1

Type RM Length L Ch R = 1 ,268     ,26.9,31.6,34.8
XS GIS Cut Line= 3
2425557.00012671717322.8587467812425620.60027131717312.410151596
2425681.24755205717189.071299748
#Sta/Elev= 30
       0 2832.04    11.3 2827.29    19.4 2825.08    23.5 2824.53    30.9 2822.62
    39.7 2821.54    43.8 2820.01    55.9 2812.42      64 2805.02    68.1 2802.58
   70.55 2801.58    72.6 2800.81      77 2800.89    81.5 2801.58    87.5 2802.45
    94.8  2804.4   103.7 2803.79   108.2 2804.47   120.3 2810.02     126 2810.93
   153.2 2811.53   166.1 2812.63   170.6 2811.95     175 2810.43   179.5  2810.1
   181.3 2810.42   183.9 2811.04   189.1 2813.73   192.9 2816.53   201.9 2824.95
#Mann= 5, -1 ,  0
       0    0.06       0   70.55   0.045       0    81.5    0.06       0
  114.45    0.07       0  154.45    0.06       0
#XS Ineff= 2 , 0
                           94.62          2805.8
Permanent Ineff=
       F       F
Bank Sta=70.55,81.5
XS Rating Curve= 0 ,0
Exp/Cntr(USF)=0,0
Exp/Cntr=0.3,0.1

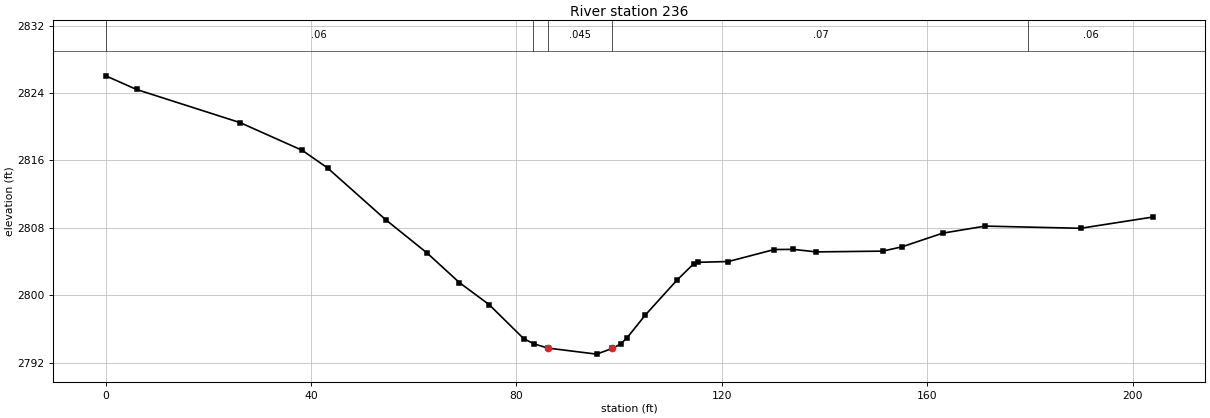
Type RM Length L Ch R = 1 ,236     ,,,
XS GIS Cut Line= 4
 2425566.2053178717334.3611129692425628.78276534717325.626595345
2425676.57625927717295.4175001262425695.30020422717213.245094541
#Sta/Elev= 30
       0 2826.03       6 2824.41    26.2 2820.47    38.3 2817.18    43.2  2815.1
    54.5 2808.97    62.6    2805    68.9 2801.49    74.7 2798.87    81.4 2794.85
    83.4 2794.23    86.1 2793.73    95.6 2793.01   98.69 2793.69   100.3 2794.22
   101.5 2794.92   105.1 2797.65   111.2 2801.75   114.5 2803.72   115.3  2803.9
   121.3    2804   130.2 2805.42   133.9 2805.44   138.4 2805.14   151.3 2805.23
   155.1 2805.74     163 2807.36   171.3  2808.2   189.9 2807.94     204 2809.28
#Mann= 5, -1 ,  0
       0    0.06       0   83.18    0.07       0    86.1   0.045       0
   98.69    0.07       0  179.72    0.06       0
Bank Sta=86.1,98.69
XS Rating Curve= 0 ,0
Exp/Cntr(USF)=0,0
Exp/Cntr=0.3,0.1
LCMann Table=0

Chan Stop Cuts=-1
Use User Specified Reach Order=0
Composite Channel Slope=5